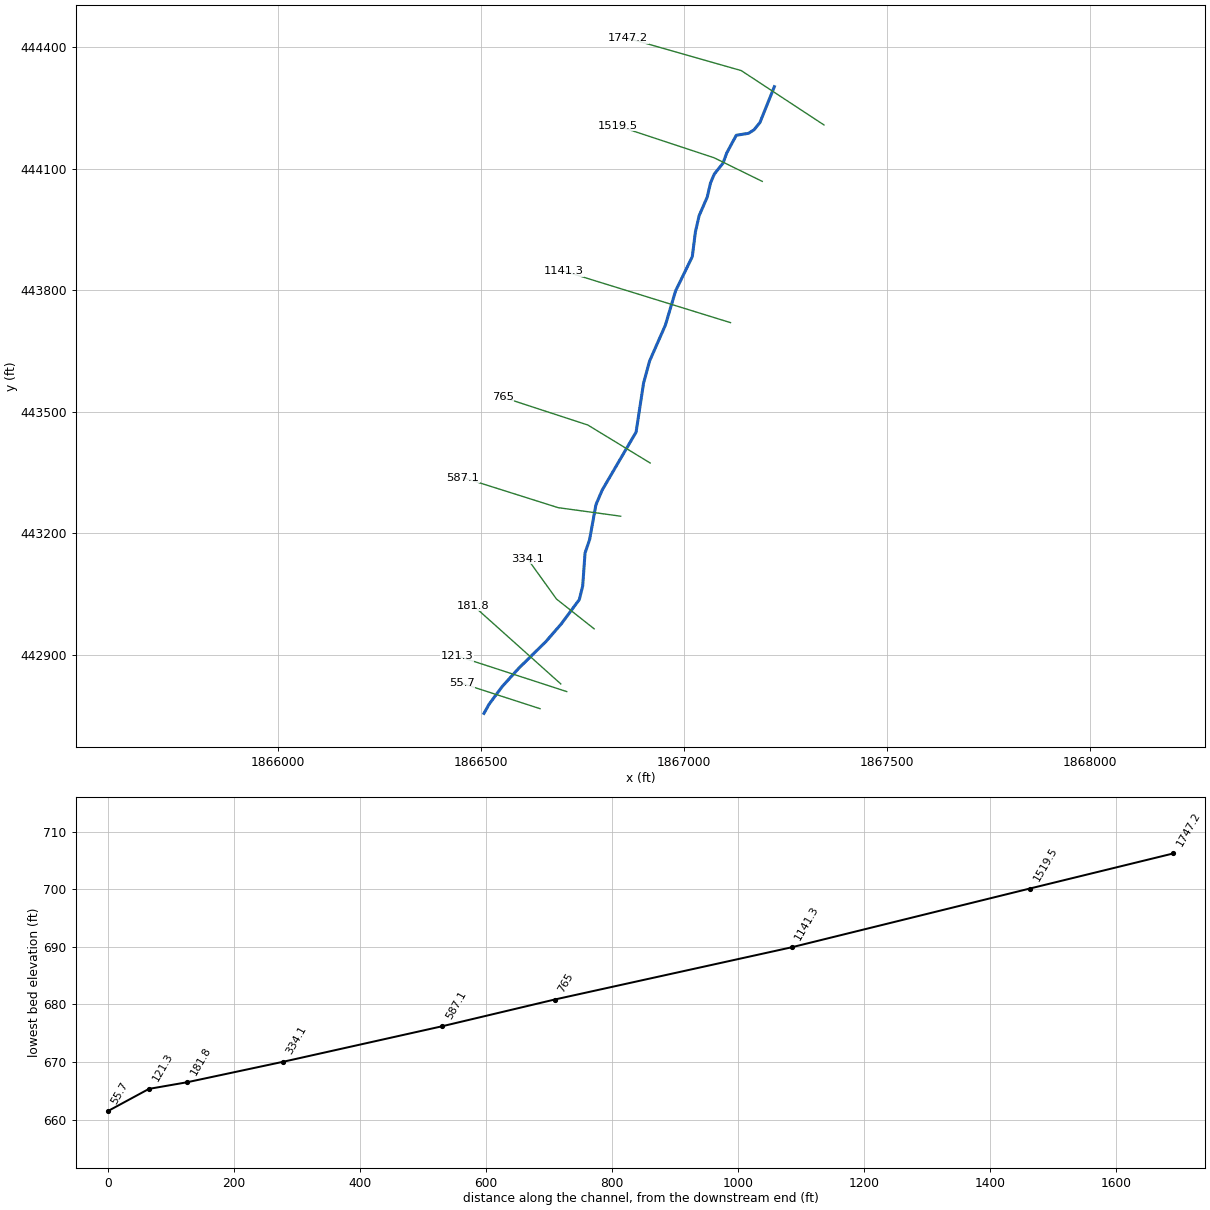
--- BUFFLICKCK.prj (project) ---

Proj Title=BUFFLICKCK
Current Plan=p01
Default Exp/Contr=0,0
English Units
Geom File=g01
Flow File=f01
Plan File=p01
BEGIN DESCRIPTION:
END DESCRIPTION:
DSS Export Rating Curves= 0
DSS Export Rating Curve Sorted= 0
DSS Export Volume Flow Curves= 0
DXF OffsetX= 0
DXF OffsetY= 0
DXF ScaleX= 0
DXF ScaleY= 0

--- BUFFLICKCK.p01 (plan) ---

Plan Title=Floodplain
Program Version=4.00
Geom File=g01
Flow File=f01
K Sum by GR=0
Std Step Tol=0.01
Critical Tol=0.01
Num of Std Step Trials=20
Max Error Tol=0.3
Flow Tol Ratio=0.001
Split Flow NTrial=30
Split Flow Tol=0.02
Split Flow Ratio=0.02
Log Output Level=0
Friction Slope Method=1
Unsteady Friction Slope Method=2
Unsteady Bridges Friction Slope Method=1
Global Log Level=0
CheckData=False
Run HTab=0
Run UNet=0
Run PostProcess=0
UNET Theta=0
UNET Theta Warmup=0
UNET ZTol=0
UNET ZSATol=0
UNET MxIter=0
UNET MaxInSteps=0
UNET DtIC=0
UNET DtMin=0
UNET MaxCRTS=0
UNET WFStab=0
UNET SFStab=0
UNET WFX=0
UNET SFX=0
UNET DSS MLevel=0
UNET DZMax Abort=0
UNET Convert EG Bridges=0
UNET Use Existing IB Tables=0
UNET Froude Limit=0
UNET Froude Power=0
Write IC File=0
Echo Input=False
Echo Output=False
Write Detailed=0

--- BUFFLICKCK.f01 (steady flow) ---

Flow Title=NFF Regression Equation
Program Version=4.10
Number of Profiles= 1
Profile Names=P100yr
River Rch & RM=BUFFLICKCK,Main            ,1747.2
894.3459
River Rch & RM=BUFFLICKCK,Main            ,587.1
918.3644
Boundary for River Rch & Prof#=BUFFLICKCK,Main            , 1
Up Type= 0
Dn Type= 3
Dn Slope=0.06
DSS Import GetInterval= 0
DSS Import GetPeak= 0
DSS Import FillOption= 0

--- BUFFLICKCK.g01 (geometry) ---

Geom Title=USGS 10m DEM
Program Version=4.10

River Reach=BUFFLICKCK      ,Main
Reach XY= 30
     1867222.879       444302.95     1867187.355      444214.489
     1867172.771      444196.433      1867159.23      444187.753
     1867129.021      444182.892     1867105.478      444139.137
     1867096.383      444114.142     1867074.855      444087.058
     1867065.607      444065.307     1867057.494      444030.461
     1867037.355      443983.933     1867028.327      443944.003
     1867020.688      443883.239     1866979.617      443798.934
     1866954.369      443714.142      1866915.48        443625.6
      1866900.65      443571.078     1866882.259      443450.219
     1866798.786      443307.218     1866783.248       443270.64
      1866767.69      443184.675       1866756.5      443151.535
     1866750.742      443070.451     1866742.392      443036.751
     1866697.674      442976.382     1866659.897      442932.869
     1866593.708      442867.765     1866552.449      442822.089
      1866520.39      442778.876     1866507.423      442755.821

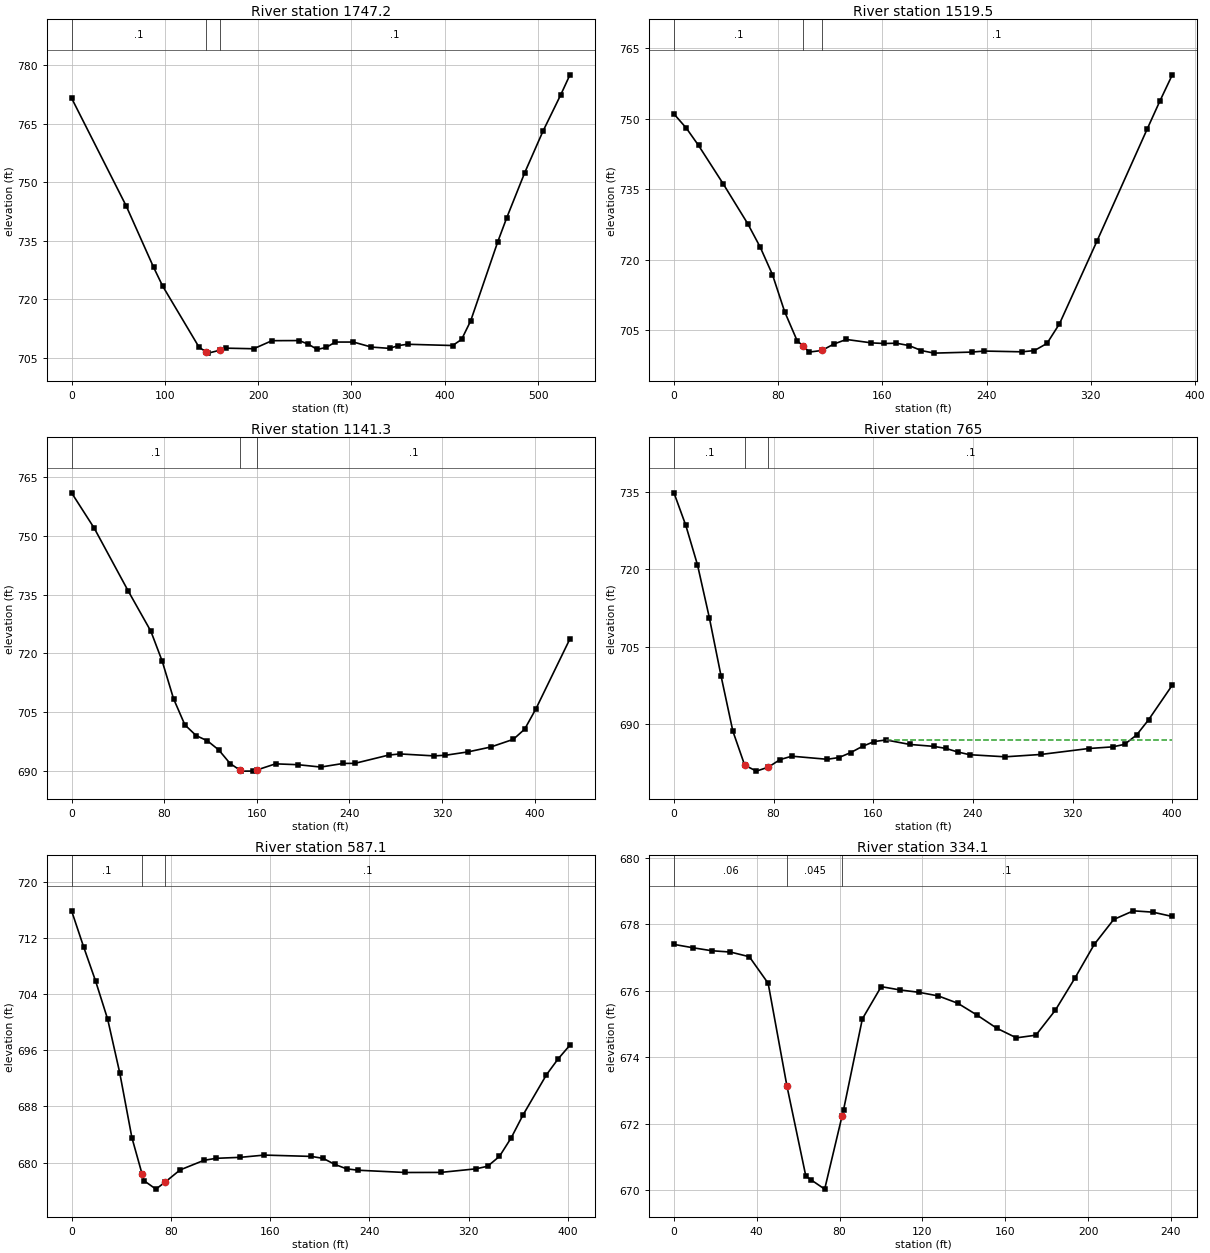
Type RM Length L Ch R = 1 ,1747.2  ,222.5,227.7,231.6
XS GIS Cut Line= 3
     1867345.163      444208.342     1867141.353       444342.59
     1866862.351      444422.231
#Sta/Elev= 30
       0  771.57    58.6   743.9    87.9  728.21    97.6   723.4   136.7  707.69
   144.1  706.55   146.4   706.2   159.1  706.95     166  707.47   195.2  707.32
   214.8  709.39     244  709.42   253.7  708.49   263.4  707.14   273.1  707.68
   282.7  709.04   302.1  709.04   321.4  707.75   340.8  707.42   350.4  708.14
   360.1  708.47   408.5  708.15   418.1  709.73   427.8  714.47   456.8  734.72
   466.5  740.93   485.8  752.49   505.2  763.04   524.5  772.49   534.2  777.54
#Mann= 3 , 0 , 0
       0      .1       0   144.1    .045       0   159.1      .1       0
#XS Ineff= 2 , 0
                          215.18          709.36
Permanent Ineff=
       F       F
Bank Sta=144.1,159.1
XS Rating Curve= 0 ,0
Exp/Cntr=0.3,0.1

Type RM Length L Ch R = 1 ,1519.5  ,374.5,378.2,381.3
XS GIS Cut Line= 3
     1867193.025      444069.117     1867074.275       444127.45
     1866836.775      444206.096
#Sta/Elev= 30
       0  751.01     9.4  748.03    18.9   744.3    37.8  736.14    56.7  727.62
    66.2  722.67    75.6  716.82      85   708.9    94.5  702.78    99.3  701.55
     104  700.34   113.4  700.67   122.8  702.05   132.3  703.02   151.6  702.29
   161.2  702.16   170.8  702.22   180.4  701.72     190  700.65   199.7  700.11
   228.5  700.33   238.2  700.55     267  700.39   276.6  700.65   286.3  702.17
   295.9  706.35   324.8  724.03   363.2  747.79   372.9  753.72   382.5  759.34
#Mann= 3 , 0 , 0
       0      .1       0    99.3    .045       0   113.4      .1       0
#XS Ineff= 2 , 0
                          132.61          702.95
Permanent Ineff=
       F       F
Bank Sta=99.3,113.4
XS Rating Curve= 0 ,0
Exp/Cntr=0.3,0.1

Type RM Length L Ch R = 1 ,1141.3  ,381.7,376.3,370.4
XS GIS Cut Line= 2
     1867114.844      443720.406     1866703.531      443847.849
#Sta/Elev= 30
       0  760.97    19.6  751.93    48.9  735.92    68.5  725.63    78.3  717.98
    88.1   708.4    97.9  701.72   107.6  698.99   117.4  697.64   127.2  695.31
     137  691.84   145.2  690.23   146.8  689.91   156.6  689.92   160.2  690.21
   176.2  691.77   195.7  691.55   215.3  690.95   234.9  691.88   244.7  691.89
     274  694.01   283.8   694.3   313.2   693.8     323  693.96   342.5  694.82
   362.1  696.06   381.7  698.03   391.5  700.63   401.2  705.81   430.6  723.68
#Mann= 3 , 0 , 0
       0      .1       0   145.2    .045       0   160.2      .1       0
Bank Sta=145.2,160.2
XS Rating Curve= 0 ,0
Exp/Cntr=0.3,0.1

Type RM Length L Ch R = 1 ,765     ,168.5,177.9,187.1
XS GIS Cut Line= 3
     1866916.797      443373.983     1866763.348      443467.673
     1866553.976      443536.238
#Sta/Elev= 30
       0  734.88     9.5  728.57    18.9  720.89    28.4  710.65    37.8  699.33
    47.3   688.6    56.8  681.99    66.2  680.84    75.7  681.61    85.2  683.08
    94.6  683.74     123  683.14   132.5  683.48   141.9  684.44   151.4  685.66
   160.9  686.59   170.3  686.89   189.4  686.02   208.5  685.65   218.1  685.26
   227.7  684.57   237.3  684.03     266  683.62   294.7  684.08     333  685.23
   352.2  685.55   361.8  686.04   371.4  687.85     381  690.79   400.1  697.54
#Mann= 3 , 0 , 0
       0      .1       0    56.8    .045       0    75.7      .1       0
#XS Ineff= 2 , 0
                          170.12          686.93
Permanent Ineff=
       F       F
Bank Sta=56.8,75.7
XS Rating Curve= 0 ,0
Exp/Cntr=0.3,0.1

Type RM Length L Ch R = 1 ,587.1   ,264.8,253,240.7
XS GIS Cut Line= 3
     1866844.271      443242.588     1866690.303      443263.641
     1866455.454       443337.96
#Sta/Elev= 30
       0  715.87     9.7  710.74    19.4  705.84    29.1  700.42    38.8   692.8
    48.6  683.57    56.7 678.446    58.3  677.43      68  676.22    75.6677.2478
    87.4  678.95   106.8  680.33   116.6  680.61     136  680.75   155.4  681.07
   193.3  680.88   202.8   680.6   212.2  679.74   221.7  679.11   231.2  678.91
   269.1  678.59   297.5   678.6   325.9  679.11   335.4  679.48   344.9  680.89
   354.4  683.54   363.8  686.76   382.8  692.52   392.2  694.78   401.7  696.73
#Mann= 3 , 0 , 0
       0      .1       0    56.7    .045       0    75.6      .1       0
#XS Ineff= 2 , 0
                          156.53          680.76
Permanent Ineff=
       F       F
Bank Sta=56.7,75.6
XS Rating Curve= 0 ,0
Exp/Cntr=0.3,0.1

Type RM Length L Ch R = 1 ,334.1   ,153.3,152.3,150.5
XS GIS Cut Line= 3
     1866778.872      442964.589     1866686.163      443038.026
     1866614.809      443137.505
#Sta/Elev= 29
       0   677.4     9.1   677.3    18.2  677.21    27.3  677.17    36.4  677.03
    45.5  676.23    54.6  673.13    63.7  670.43    66.2  670.32    72.8  670.04
    81.2  672.24    81.9  672.42      91  675.16   100.1  676.13   109.2  676.03
   118.3  675.96   127.7  675.85   137.1  675.63   146.5  675.27   155.9  674.88
   165.4  674.59   174.8  674.67   184.2  675.42   193.6  676.38     203   677.4
   212.4  678.15   221.9  678.41   231.3  678.37   240.7  678.24
#Mann= 3 , 0 , 0
       0     .06       0    54.6    .045       0    81.2      .1       0
Bank Sta=54.6,81.2
XS Rating Curve= 0 ,0
Exp/Cntr=0.3,0.1

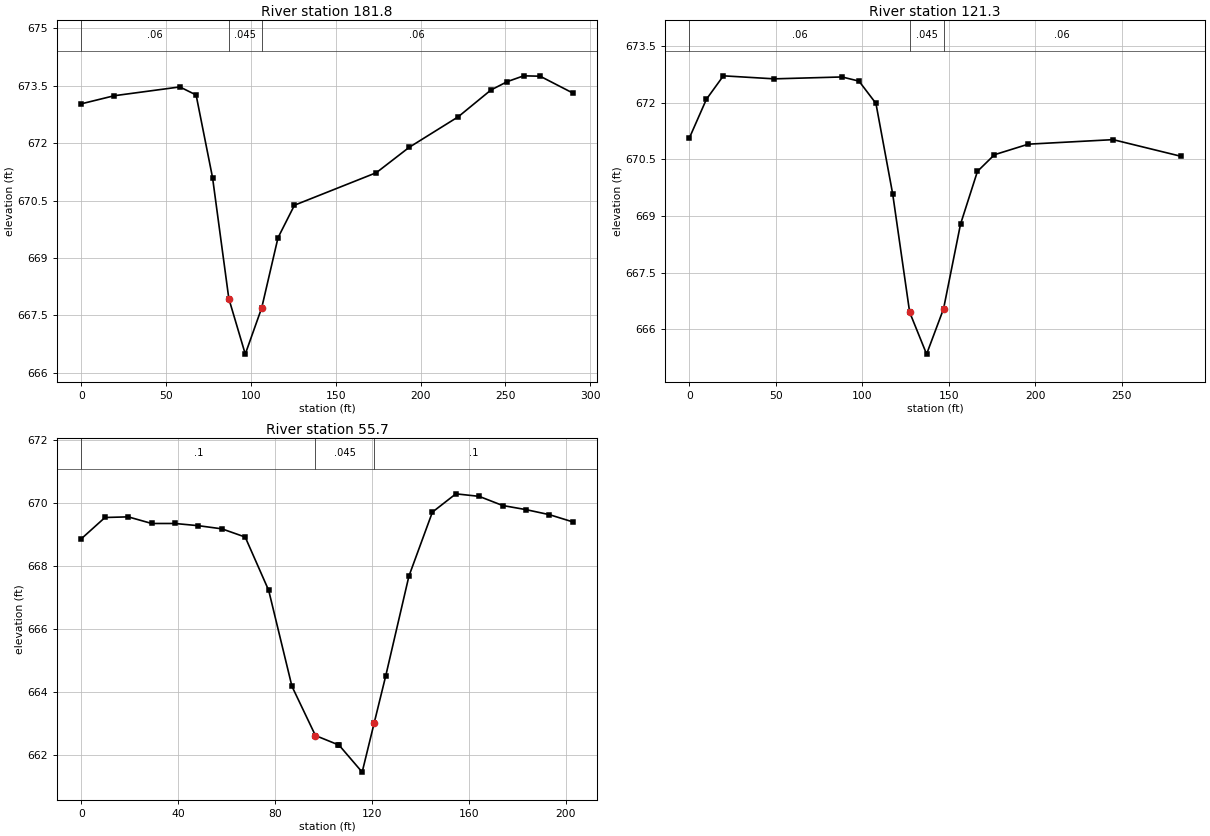
Type RM Length L Ch R = 1 ,181.8   ,50.6,60.5,70.5
XS GIS Cut Line= 2
     1866696.698      442828.571     1866480.987      443022.084
#Sta/Elev= 18
       0  673.03    19.3  673.24      58  673.47    67.6  673.26    77.3   671.1
    86.9  667.94    96.6  666.49   106.3   667.7   115.9  669.53   125.6  670.38
   173.9  671.23   193.2  671.89   222.2  672.69   241.5  673.39   251.2  673.61
   260.8  673.76   270.5  673.75   289.8  673.31
#Mann= 3 , 0 , 0
       0     .06       0    86.9    .045       0   106.3     .06       0
Bank Sta=86.9,106.3
XS Rating Curve= 0 ,0
Exp/Cntr=0.3,0.1

Type RM Length L Ch R = 1 ,121.3   ,65.8,65.6,65.2
XS GIS Cut Line= 2
     1866711.356      442809.639     1866441.261      442897.632
#Sta/Elev= 17
       0  671.07     9.8  672.09    19.6  672.71      49  672.63    88.2  672.68
      98  672.57   107.8  671.98   117.5  669.58   127.3  666.45   137.1  665.34
   146.9  666.54   156.7  668.78   166.5  670.18   176.3  670.62   195.9   670.9
   244.9  671.02   284.1  670.58
#Mann= 3 , 0 , 0
       0     .06       0   127.3    .045       0   146.9     .06       0
Bank Sta=127.3,146.9
XS Rating Curve= 0 ,0
Exp/Cntr=0.3,0.1

Type RM Length L Ch R = 1 ,55.7    ,60.5,55.7,51
XS GIS Cut Line= 2
     1866645.739      442767.395      1866452.77      442829.979
#Sta/Elev= 24
       0  668.86     9.7  669.53    19.3  669.55      29  669.34    38.6  669.34
    48.3  669.27      58  669.17    67.6  668.91    77.3  667.22    86.9  664.18
    96.6  662.62   105.9  662.33   106.3  662.32   115.9  661.46   120.9  663.03
   125.6   664.5   135.2  667.67   144.9   669.7   154.6  670.28   164.2   670.2
   173.9  669.91   183.5  669.78   193.2  669.62   202.9  669.39
#Mann= 3 , 0 , 0
       0      .1       0    96.6    .045       0   120.9      .1       0
Bank Sta=96.6,120.9
XS Rating Curve= 0 ,0
Exp/Cntr=0.3,0.1

Chan Stop Cuts=-1
Use User Specified Reach Order=0
Composite Channel Slope=5